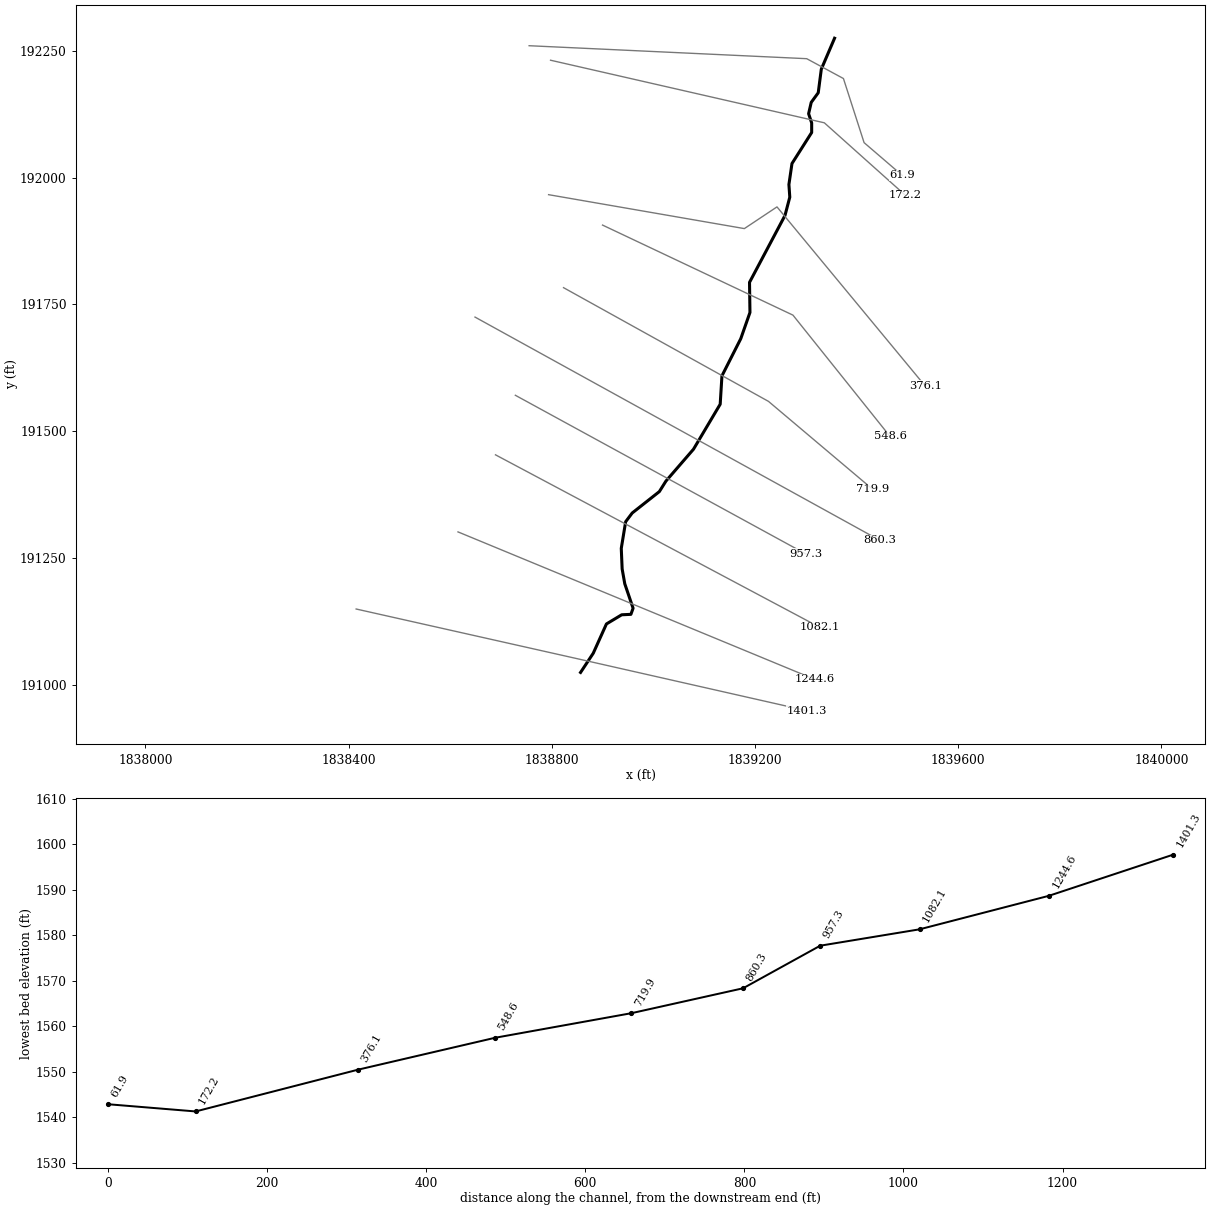
--- LaurelBr2.prj (project) ---

Proj Title=LaurelBr2
Current Plan=p01
Default Exp/Contr=0,0
English Units
Geom File=g01
Flow File=f01
Plan File=p01
BEGIN DESCRIPTION:
END DESCRIPTION:
DSS Export Rating Curves= 0
DSS Export Rating Curve Sorted= 0
DSS Export Volume Flow Curves= 0
DXF OffsetX= 0
DXF OffsetY= 0
DXF ScaleX= 0
DXF ScaleY= 0

--- LaurelBr2.p01 (plan) ---

Plan Title=Floodplain
Program Version=4.00
Geom File=g01
Flow File=f01
K Sum by GR=0
Std Step Tol=0.01
Critical Tol=0.01
Num of Std Step Trials=20
Max Error Tol=0.3
Flow Tol Ratio=0.001
Split Flow NTrial=30
Split Flow Tol=0.02
Split Flow Ratio=0.02
Log Output Level=0
Friction Slope Method=1
Unsteady Friction Slope Method=2
Unsteady Bridges Friction Slope Method=1
Global Log Level=0
CheckData=False
Run HTab=0
Run UNet=0
Run PostProcess=0
UNET Theta=0
UNET Theta Warmup=0
UNET ZTol=0
UNET ZSATol=0
UNET MxIter=0
UNET MaxInSteps=0
UNET DtIC=0
UNET DtMin=0
UNET MaxCRTS=0
UNET WFStab=0
UNET SFStab=0
UNET WFX=0
UNET SFX=0
UNET DSS MLevel=0
UNET DZMax Abort=0
UNET Convert EG Bridges=0
UNET Use Existing IB Tables=0
UNET Froude Limit=0
UNET Froude Power=0
Write IC File=0
Echo Input=False
Echo Output=False
Write Detailed=0

--- LaurelBr2.f01 (steady flow) ---

Flow Title=NFF Regression Equation
Program Version=4.00
Number of Profiles=1
Profile Names=P100yr
River Rch & RM=LaurelBr2,Main      ,1401.3
500.1836
River Rch & RM=LaurelBr2,Main      ,1082.1
686.3092
River Rch & RM=LaurelBr2,Main      ,172.2
698.0247
Boundary for River Rch & Prof#=LaurelBr2,Main      ,1
Up Type=0
Dn Type=3
Dn Slope=0.030807

--- LaurelBr2.g01 (geometry) ---

Geom Title=USGS 10m DEM
Program Version=4.00

River Reach=LaurelBr2       ,Main
Reach XY= 30
     1838856.596       191024.11     1838881.583      191062.021
     1838907.517      191119.746     1838937.589      191137.844
     1838955.683      191138.706     1838959.991      191150.769
      1838943.62       191199.02      1838938.45      191228.315
     1838936.727      191268.811     1838945.343       191321.37
     1838958.268      191338.603     1839011.688      191380.822
     1839024.613      191401.501     1839078.895        191464.4
     1839131.454      191553.147     1839134.901      191609.153
     1839171.951      191682.391     1839190.045      191734.088
     1839189.183      191793.541     1839258.975      191925.369
     1839268.453      191961.557     1839266.729      191986.545
     1839272.761      192027.902     1839311.534      192089.078
     1839311.534      192108.033     1839305.502      192126.128
     1839310.672       192148.53     1839324.458      192167.486
      1839330.49      192214.013     1839356.606      192275.084

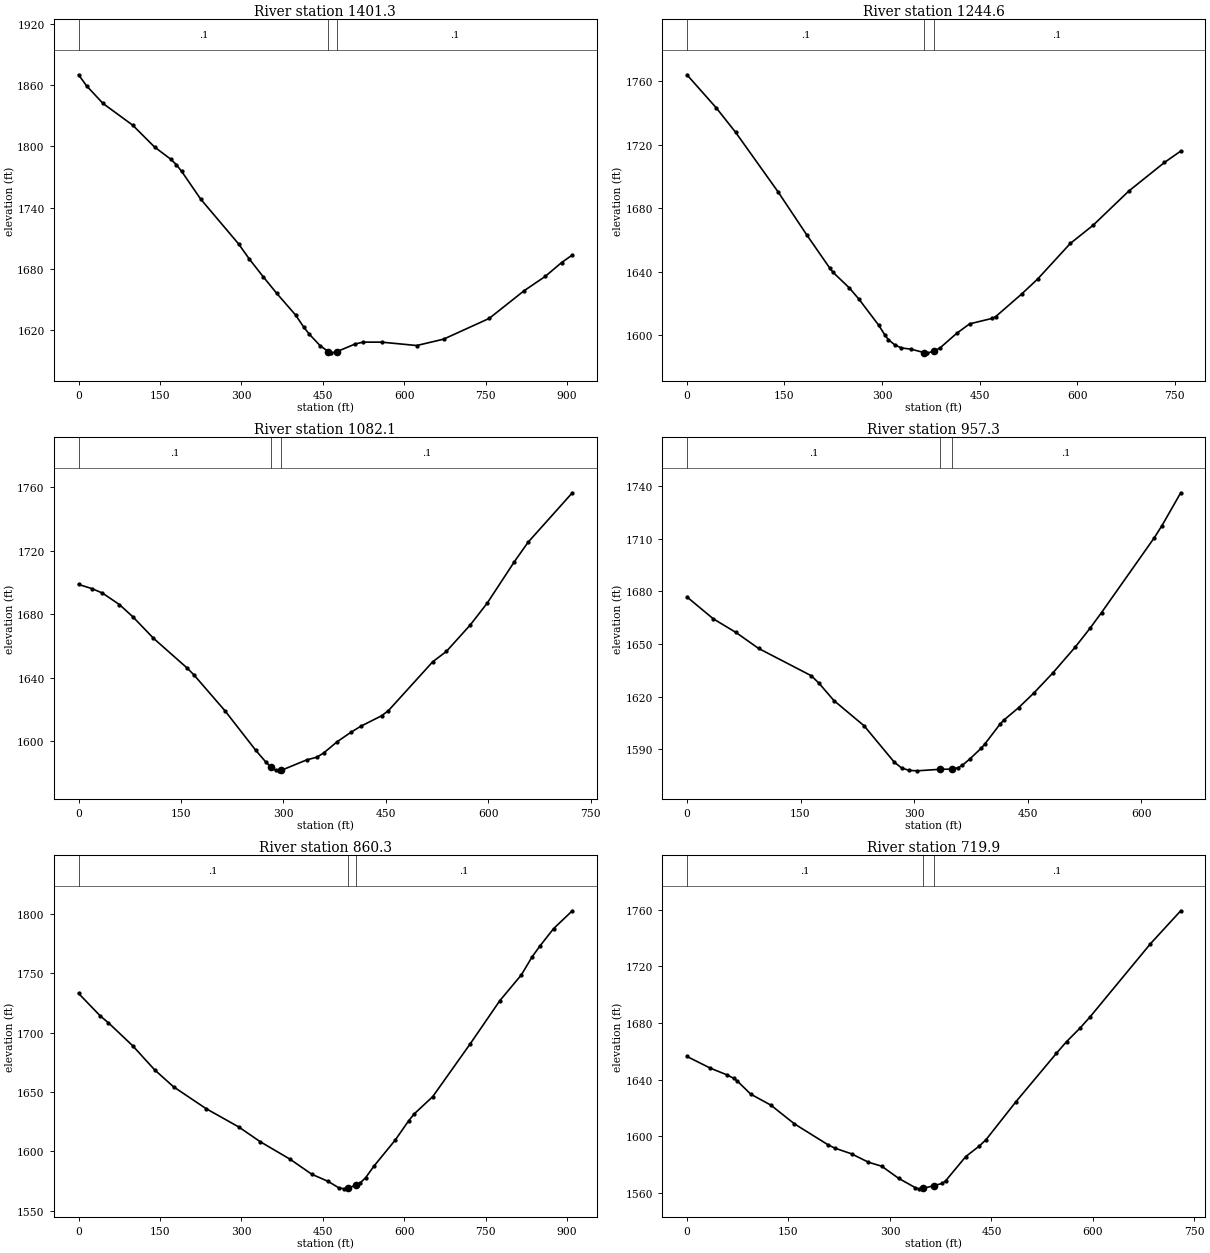
Type RM Length L Ch R = 1 ,1401.3  ,160.9,156.7,153.4
XS GIS Cut Line= 3
     1838414.834      191149.234     1838858.717      191049.273
     1839302.428      190948.541
#Sta/Elev= 30
       0 1870.17      15 1859.22      45 1842.11     100 1820.71     140 1799.44
     170 1787.42     180 1782.26     190 1775.56     225 1748.43     295 1704.45
     315 1689.46     340 1672.53     365 1656.19     400 1634.79     415    1623
     425 1616.21     445 1604.88   460.4 1598.96   464.9 1597.76   475.4 1598.77
   509.4 1606.34   524.2 1608.27   558.9 1608.22   623.2 1604.93   672.6 1611.13
   756.7 1631.45     821 1658.55   860.5  1672.8   890.2  1686.2     910 1693.59
#Mann= 3 , 0 , 0
       0      .1       0   460.4    .045       0   475.4      .1       0
Bank Sta=460.4,475.4
XS Rating Curve= 0 ,0
Exp/Cntr=0.3,0.1

Type RM Length L Ch R = 1 ,1244.6  ,162.3,162.5,161.3
XS GIS Cut Line= 2
      1838615.33      191301.321     1839316.861      191010.773
#Sta/Elev= 30
       0 1764.13      45  1743.3    74.9 1727.79   139.9 1690.39   184.8 1662.77
   219.8 1642.05   224.8 1639.43   249.8  1629.6   264.8  1622.4   294.7 1606.21
   304.7 1599.71   309.7 1597.03   319.7 1593.67   329.7  1591.8   344.7 1590.97
   364.4 1588.89   369.7 1588.68   379.4 1589.58   389.6 1591.93   414.6 1600.93
   434.6 1606.96   469.6 1610.45   474.6 1611.48   514.5 1625.73   539.5 1635.34
   589.5  1657.7   624.4 1669.12   679.4 1690.75   734.3 1708.81   759.3 1715.98
#Mann= 3 , 0 , 0
       0      .1       0   364.4    .045       0   379.4      .1       0
Bank Sta=364.4,379.4
XS Rating Curve= 0 ,0
Exp/Cntr=0.3,0.1

Type RM Length L Ch R = 1 ,1082.1  ,125,124.8,124.6
XS GIS Cut Line= 2
     1838689.096       191453.37     1839327.399      191113.142
#Sta/Elev= 30
       0 1698.65      20 1695.96    34.9 1693.24    59.9 1685.96    79.8 1678.18
   109.7 1664.78   159.6 1645.83   169.6 1641.43   214.5 1619.11   259.4 1594.33
   274.4 1586.82   282.1  1583.6   289.3 1581.55   294.3 1581.31   297.1 1581.65
   334.2 1588.21   349.2 1589.91   359.2 1592.62   379.1 1599.71   399.1 1605.61
     414  1609.5     444 1615.99   453.9  1619.2   518.8 1649.96   538.8 1656.48
   573.7 1673.09   598.6 1686.86   638.5 1713.01   658.5 1725.21   723.3 1756.34
#Mann= 3 , 0 , 0
       0      .1       0   282.1    .045       0   297.1      .1       0
Bank Sta=282.1,297.1
XS Rating Curve= 0 ,0
Exp/Cntr=0.3,0.1

Type RM Length L Ch R = 1 ,957.3   ,97.1,97,96.9
XS GIS Cut Line= 2
     1838728.237      191570.793     1839300.301      191257.664
#Sta/Elev= 30
       0 1676.89    34.8 1664.41    64.7 1656.64    94.6 1647.53   164.3 1631.93
   174.2 1627.77   194.2 1617.76     234  1603.4   273.8 1582.68   283.8 1579.26
   293.7 1577.98   303.7 1577.71   334.9 1578.61   349.9 1578.66   358.4 1579.53
   363.4 1580.77   373.4 1584.38   388.3 1590.46   393.3 1592.91   413.2 1604.17
   418.2 1606.51   438.1 1613.75     458 1621.99   482.9 1633.36   512.8 1648.26
   532.7 1659.19   547.6 1667.98   617.3 1710.66   627.3 1717.47   652.2 1736.29
#Mann= 3 , 0 , 0
       0      .1       0   334.9    .045       0   349.9      .1       0
Bank Sta=334.9,349.9
XS Rating Curve= 0 ,0
Exp/Cntr=0.3,0.1

Type RM Length L Ch R = 1 ,860.3   ,140.3,140.3,139.7
XS GIS Cut Line= 3
     1838648.813      191725.036     1839047.048      191504.959
     1839445.282      191284.881
#Sta/Elev= 30
       0  1733.2      40 1714.19      55 1708.42     100 1688.92     140 1668.82
     175 1654.43     235    1636     295  1620.6     335 1608.04     390 1593.28
     430 1580.59     460 1574.64   479.7 1569.18   489.6 1568.34   496.7 1568.95
   511.7 1571.52   519.3 1573.47   529.2 1577.76     544  1587.3   583.6 1609.45
   608.3 1625.68   618.2 1631.37   652.8 1646.15   722.1 1690.84   776.5 1727.12
     816 1748.75   835.8 1763.98   850.6 1773.33   875.4 1787.79     910 1802.87
#Mann= 3 , 0 , 0
       0      .1       0   496.7    .045       0   511.7      .1       0
Bank Sta=496.7,511.7
XS Rating Curve= 0 ,0
Exp/Cntr=0.3,0.1

Type RM Length L Ch R = 1 ,719.9   ,170.7,171.4,172.9
XS GIS Cut Line= 3
     1838823.079      191783.059     1839226.535       191558.75
     1839431.274      191385.625
#Sta/Elev= 30
       0 1656.34    34.8 1648.02    59.6 1643.24    69.5 1640.77    74.4    1639
    94.3 1629.71   124.1 1621.93   158.8 1608.75   208.5 1593.96   218.4 1591.63
   243.2 1587.58     268  1581.7   287.9 1578.81   312.7 1570.32   337.5 1563.68
   342.5 1562.86   349.5 1563.28   364.5 1565.02   377.2  1566.7   382.2 1568.48
     412 1585.62   431.8 1592.99   441.8 1597.46   486.4  1624.5     546 1658.56
   560.9 1666.75   580.8 1676.31   595.7 1684.26     685 1735.93   729.7 1759.19
#Mann= 3 , 0 , 0
       0      .1       0   349.5    .045       0   364.5      .1       0
Bank Sta=349.5,364.5
XS Rating Curve= 0 ,0
Exp/Cntr=0.3,0.1

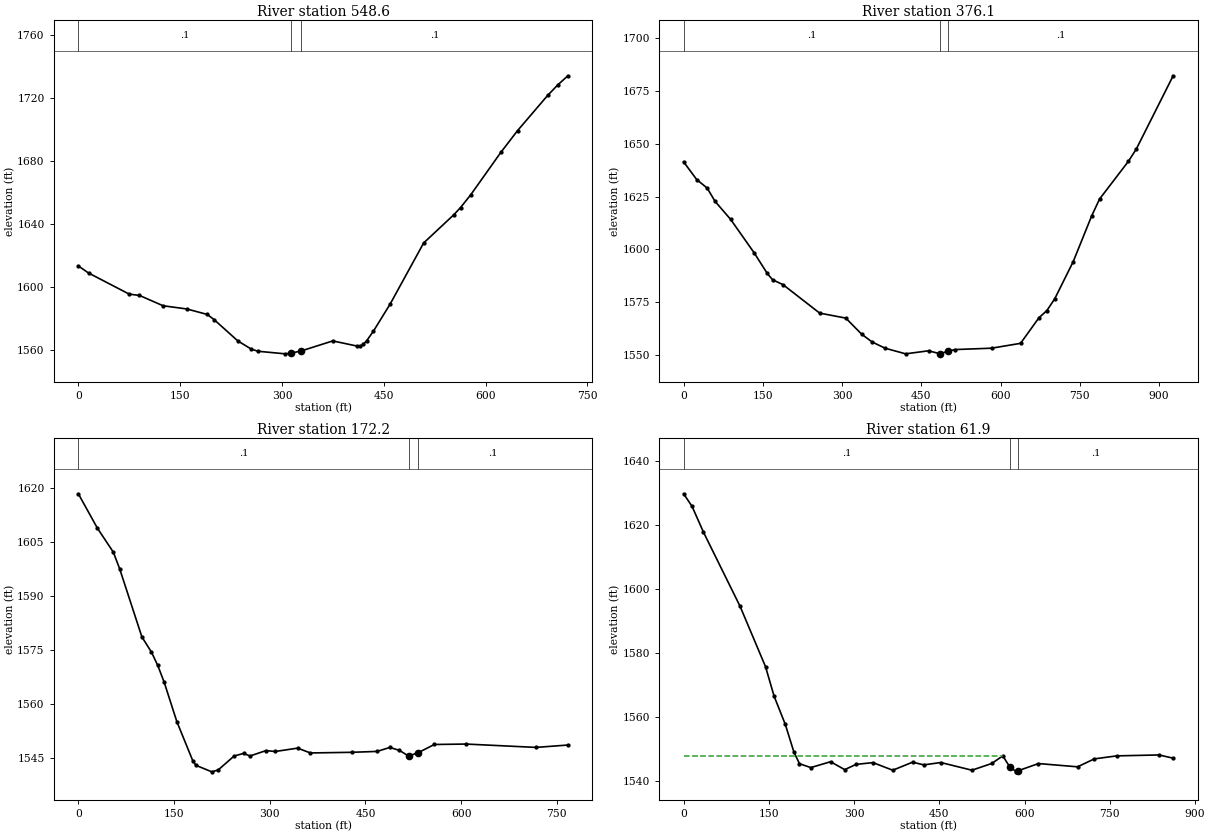
Type RM Length L Ch R = 1 ,548.6   ,178.4,172.5,162.2
XS GIS Cut Line= 3
     1838899.856      191906.504     1839274.709      191728.864
     1839465.898        191489.5
#Sta/Elev= 30
       0 1613.33      15 1608.83      75 1595.39      90 1594.58   124.9    1588
   159.9 1585.96   189.9 1582.49   199.9 1579.24   234.9 1565.69   254.9 1560.42
   264.9 1559.08   304.9 1557.45   313.5 1557.89   328.5 1559.32   374.8 1565.66
   409.8 1562.47   414.8 1562.28   419.8 1563.44   424.7 1565.73   434.6 1571.78
   459.3 1589.05   508.7  1627.9   553.2 1645.87     563 1650.41   577.9 1658.42
   622.3 1685.42     647 1699.29   691.5 1721.74   706.3 1728.37   721.2 1734.17
#Mann= 3 , 0 , 0
       0      .1       0   313.5    .045       0   328.5      .1       0
Bank Sta=313.5,328.5
XS Rating Curve= 0 ,0
Exp/Cntr=0.3,0.1

Type RM Length L Ch R = 1 ,376.1   ,193.9,203.9,218.5
XS GIS Cut Line= 4
      1838793.64      191966.471      1839179.03      191899.563
     1839243.262      191942.384     1839534.981      191589.109
#Sta/Elev= 30
       0 1641.43    24.8 1633.04    44.6 1629.02    59.4 1622.76    89.1 1614.13
   133.7 1598.24   158.4 1588.51   168.4 1585.54   188.2 1583.21   257.5 1569.73
     307 1567.36   336.7  1559.8   356.5 1556.08   381.2  1553.1   420.1 1550.42
   463.5 1551.86   484.6 1550.51   499.6 1551.56   513.2 1552.44   582.9  1553.1
   637.7  1555.4   672.5 1567.53   687.5 1570.94   702.4 1576.53   737.3 1594.11
   772.1 1615.71   787.1 1623.77   841.8  1641.7   856.8 1647.55   926.5 1682.25
#Mann= 3 , 0 , 0
       0      .1       0   484.6    .045       0   499.6      .1       0
Bank Sta=484.6,499.6
XS Rating Curve= 0 ,0
Exp/Cntr=0.3,0.1

Type RM Length L Ch R = 1 ,172.2   ,115.4,110.3,104.7
XS GIS Cut Line= 3
     1838797.487      192231.677     1839336.431      192108.232
     1839496.007      191965.216
#Sta/Elev= 30
       0  1618.4    29.9 1608.85    54.8 1602.21    64.8 1597.57    99.6 1578.68
   114.6 1574.46   124.5 1570.75   134.5 1566.12   154.4 1555.17   179.3 1544.34
   184.3 1543.05   209.2 1541.24   219.2 1541.77   244.1 1545.62     259 1546.36
     269 1545.64   293.9 1547.12   308.8 1546.89   343.7 1547.82   363.6 1546.48
   428.4 1546.66   468.2 1546.91   488.2 1548.01   503.1  1547.2   517.7 1545.61
   532.7 1546.57   557.9 1548.83   607.7 1548.95   717.4 1548.02   767.2 1548.68
#Mann= 3 , 0 , 0
       0      .1       0   517.7    .045       0   532.7      .1       0
#XS Ineff= 2 , 0
          488.09 1547.97
Permanent Ineff=
       F       F
Bank Sta=517.7,532.7
XS Rating Curve= 0 ,0
Exp/Cntr=0.3,0.1

Type RM Length L Ch R = 1 ,61.9    ,60.4,61.9,63.5
XS GIS Cut Line= 5
     1838755.335      192260.281     1839301.806      192234.688
     1839374.067      192195.547     1839414.714      192069.091
     1839489.985      192004.357
#Sta/Elev= 30
       0 1629.74    14.9 1625.79    34.8  1617.8    99.5 1594.51   144.2 1575.67
   159.2 1566.49     179 1557.63     194 1549.05   203.9 1545.37   223.8 1544.16
   258.6 1545.99   283.5 1543.52   303.4 1545.16   333.2 1545.71     368 1543.34
   402.8 1545.84   422.7 1545.01   452.6 1545.74   507.3 1543.34   542.1 1545.44
   561.6 1547.82   574.1 1544.31   585.7 1542.83   589.1  1543.2   624.4 1545.42
   693.2  1544.4   722.7 1546.88   762.1 1547.82   836.5 1548.11   861.4  1547.1
#Mann= 3 , 0 , 0
       0      .1       0   574.1    .045       0   589.1      .1       0
#XS Ineff= 2 , 0
          561.35  1547.8  626.84         1545.38
Permanent Ineff=
       F       F
Bank Sta=574.1,589.1
XS Rating Curve= 0 ,0
Exp/Cntr=0.3,0.1

Chan Stop Cuts=-1
Use User Specified Reach Order=0